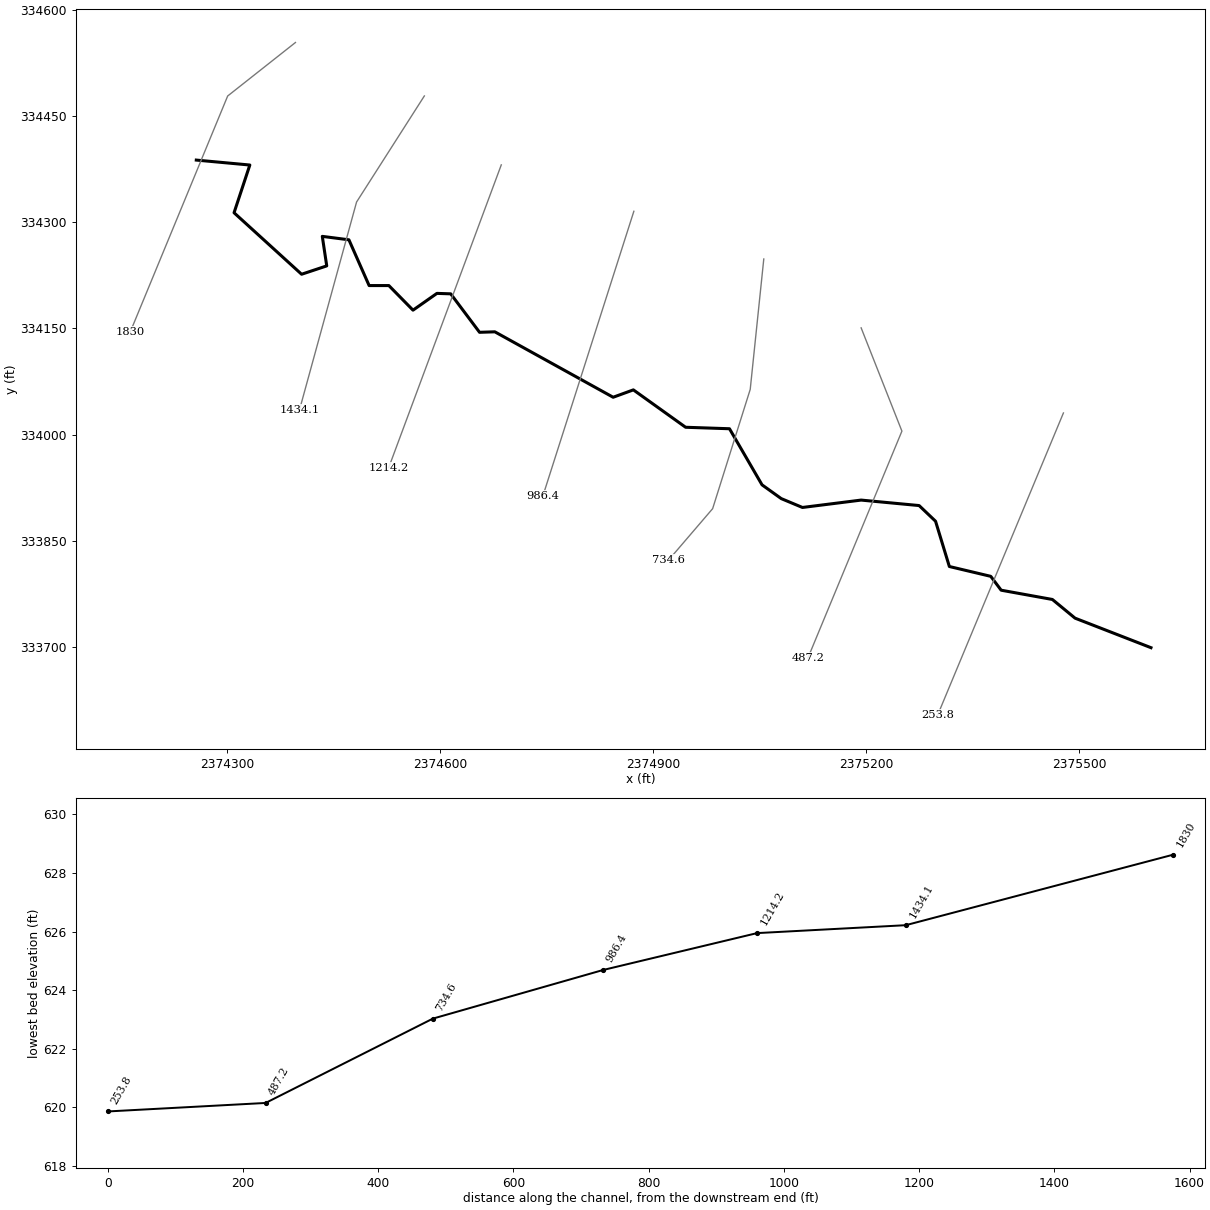
--- MIDDLECRK2.prj (project) ---

Proj Title=MIDDLECRK2
Current Plan=p01
Default Exp/Contr=0,0
English Units
Geom File=g01
Flow File=f01
Plan File=p01
BEGIN DESCRIPTION:
END DESCRIPTION:
DSS File=dss
DSS Export Rating Curves= 0
DSS Export Rating Curve Sorted= 0
DSS Export Volume Flow Curves= 0
DXF OffsetX= 0
DXF OffsetY= 0
DXF ScaleX= 0
DXF ScaleY= 0

--- MIDDLECRK2.p01 (plan) ---

Plan Title=Floodplain
Program Version=4.10
Short Identifier=Floodplain
Geom File=g01
Flow File=f01
Subcritical Flow
K Sum by GR= 0
Std Step Tol= 0.01
Critical Tol= 0.01
Num of Std Step Trials= 20
Max Error Tol= 0.3
Flow Tol Ratio= 0.001
Split Flow NTrial= 30
Split Flow Tol= 0.02
Split Flow Ratio= 0.02
Log Output Level= 0
Friction Slope Method= 1
Unsteady Friction Slope Method= 2
Unsteady Bridges Friction Slope Method= 1
Parabolic Critical Depth
Global Vel Dist= 0 , 0 , 0
Global Log Level= 0
CheckData=True
Encroach Param=-1 ,0,0, 0
Run HTab= 0
Run UNet= 0
Run PostProcess= 0
Run WQNet= 0
UNET Theta= 0
UNET Theta Warmup= 0
UNET ZTol= 0
UNET ZSATol= 0
UNET MxIter= 0
UNET MaxInSteps= 0
UNET DtIC= 0
UNET DtMin= 0
UNET MaxCRTS= 0
UNET WFStab= 0
UNET SFStab= 0
UNET WFX= 1
UNET SFX= 1
UNET DSS MLevel= 1
UNET DZMax Abort= 0
UNET Convert EG Bridges= 0
UNET Use Existing IB Tables= 0
UNET Froude Reduction=False
UNET Froude Limit= 0
UNET Froude Power= 0
UNET Time Slicing=0,0, 5
UNET Junction Losses=0
DSS File=dss
Write IC File= 0
Write IC File at Sim End=0
Echo Input=False
Echo Parameters=False
Echo Output=False
Write Detailed= 0
WQ AD Non Conservative
WQ ULTIMATE=-1
WQ Max Comp Step=1HOUR
WQ Output Interval=15MIN
WQ Output Selected Increments= 0
WQ Output face flow=0
WQ Output face velocity=0
WQ Output face area=0
WQ Output face dispersion=0
WQ Output cell volume=0
WQ Output cell surface area=0
WQ Output cell continuity=0
WQ Output cumulative cell continuity=0
WQ Output face conc=0
WQ Output face dconc_dx=0
WQ Output face courant=0
WQ Output face peclet=0
WQ Output face adv mass=0
WQ Output face disp mass=0
WQ Output cell mass=0
WQ Output cell source sink temp=0
WQ Output cell source sink nsm=0
WQ Output MaxMinRange=-1
WQ Daily Max Min Mean=-1
WQ Daily Range=0
WQ Daily Time=0
WQ Create Restart=0
WQ Fixed Restart=0
WQ System Summary=0
WQ Use Fixed Temperature=0
Sorting and Armoring Iterations= 10
XS Update Threshold= 0.02
Hydraulics Update Threshold= 0.02
Energy Slope Method= 1
Volume Change Method= 0
XS Weighting Method= 0
Number of US Weighted Cross Sections= 1
Number of DS Weighted Cross Sections= 1
Upstream XS Weight=0.25
Main XS Weight=0.5
Downstream XS Weight=0.25
Number of DS XS's Weighted with US Boundary= 1
Upstream Boundary Weight= 1
Weight of XSs Associated with US Boundary= 0
Number of US XS's Weighted with DS Boundary= 1
Downstream Boundary Weight= 0.5
Weight of XSs Associated with DS Boundary= 0.5
Sediment Output Level= 4
Mass or Volume Output= 0
Output Increment Type= 1
Profile and TS Output Increment= 10
XS Output Flag= 0
XS Output Increment= 10
Disregard all LS=0
Disregard all Conn=0
Disregard all Breaches=0
Disregard all Pumps=0

--- MIDDLECRK2.f01 (steady flow) ---

Flow Title=NFF Regression Equation
Program Version=4.10
Number of Profiles= 1
Profile Names=P100yr
River Rch & RM=MIDDLECRK2,Main            ,1830
936.0325
River Rch & RM=MIDDLECRK2,Main            ,253.8
960.6055
Boundary for River Rch & Prof#=MIDDLECRK2,Main            , 1
Up Type= 0
Dn Type= 1
Dn Known WS=624.6
DSS Import GetInterval= 0
DSS Import GetPeak= 0
DSS Import FillOption= 0

--- MIDDLECRK2.g01 (geometry) ---

Geom Title=USGS 10m DEM
Program Version=4.10

River Reach=MIDDLECRK2      ,Main
Reach XY= 30
     2374256.251      334387.588     2374331.662      334380.606
      2374309.44      334313.245     2374404.579      334226.439
     2374439.995      334238.245     2374433.745      334279.911
     2374471.245       334275.05     2374499.718      334210.467
     2374527.495      334210.467     2374561.523      334175.745
     2374595.227      334199.437      2374614.65      334198.786
     2374655.273      334144.495     2374676.801      334145.189
     2374843.468      334052.828      2374871.94      334063.245
     2374945.551      334010.467     2375007.356      334008.383
      2375053.19      333929.217     2375080.273      333909.772
     2375110.134      333897.272     2375192.773      333907.689
      2375274.48      333899.957     2375297.634      333877.828
     2375317.079      333813.939     2375375.412       333800.05
      2375390.04      333780.491     2375462.217      333767.411
     2375494.162      333741.022     2375601.107      333699.356

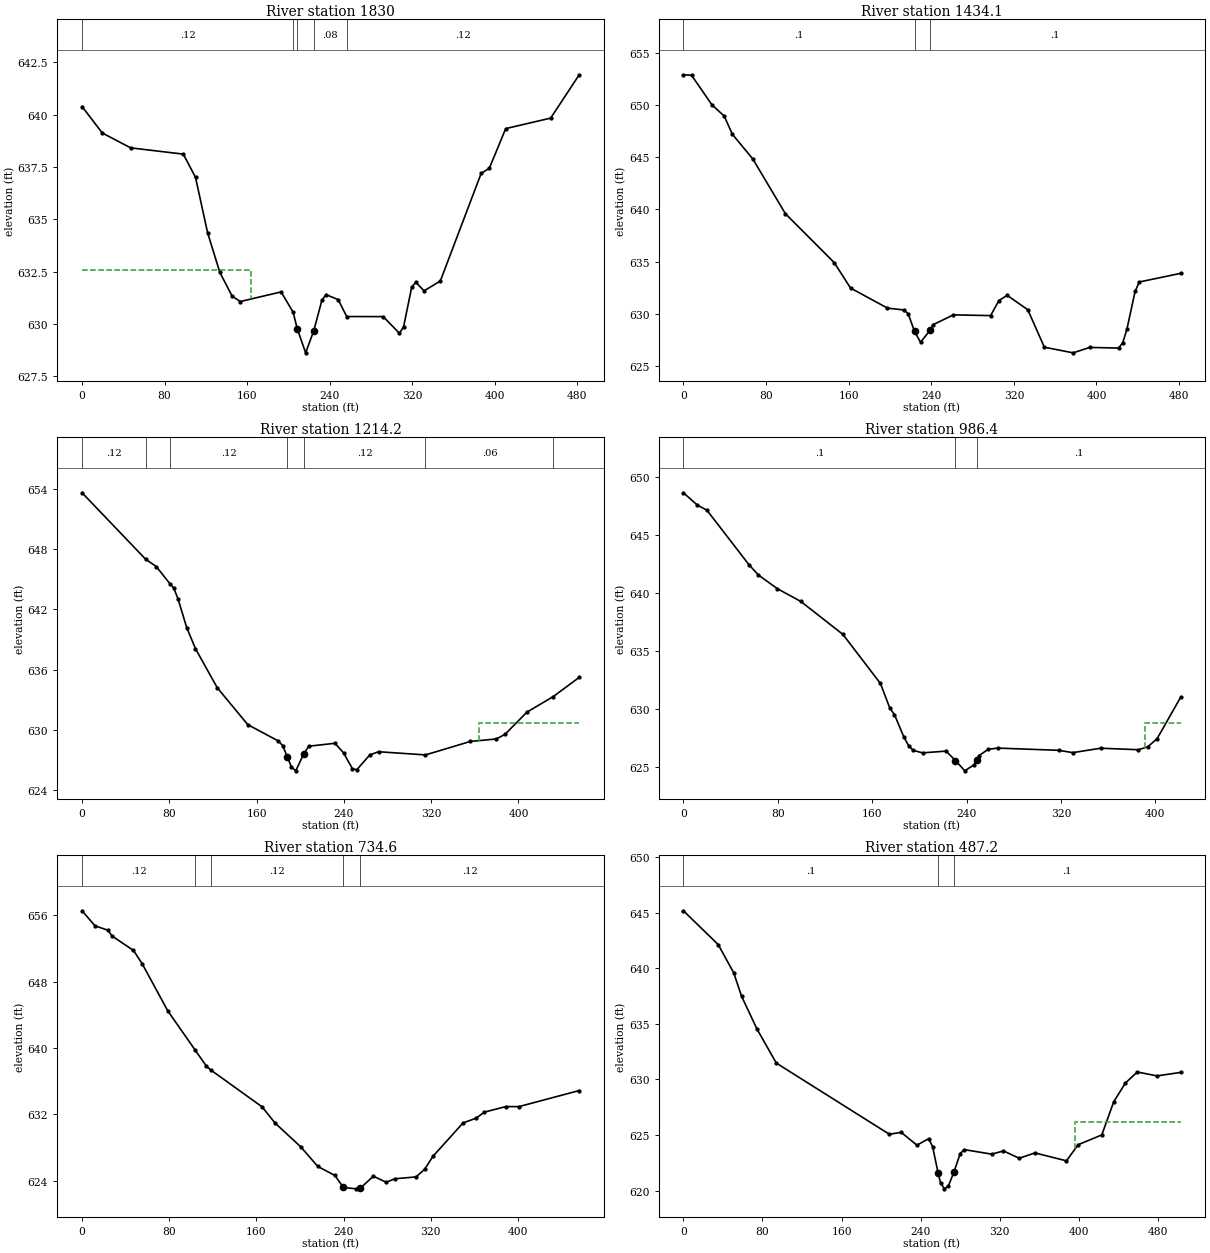
Type RM Length L Ch R = 1 ,1830    ,419.7,395.9,372.3
XS GIS Cut Line= 3
     2374395.941      334553.551     2374300.455       334478.03
     2374163.176      334144.883
#Sta/Elev= 30
       0  640.39    19.6  639.13    47.1  638.42    98.2  638.12     110  637.01
   121.7  634.37   133.6  632.47   145.5  631.34   153.4  631.08     193  631.54
  204.62630.5743   208.8  629.76   216.8  628.63   224.7  629.69   232.6  631.15
   236.6  631.41   248.4  631.17   256.6630.3638     292  630.36   307.8  629.56
   311.8  629.88   319.7  631.78   323.7     632   331.6  631.59   347.4  632.06
     387   637.2     395  637.45   410.8  639.34   454.4  639.84   482.1  641.91
#Mann= 5 ,-1 , 0
       0     .12       0  204.62     .08       0   208.8    .045       0
   224.7     .08       0   256.6     .12       0
#XS Ineff= 2 , 0
          164.09  632.61
Permanent Ineff=
       F       F
Bank Sta=208.8,224.7
XS Rating Curve= 0 ,0
Exp/Cntr=0.3,0.1

Type RM Length L Ch R = 1 ,1434.1  ,214.6,219.9,215.3
XS GIS Cut Line= 3
     2374577.501      334478.098     2374482.015      334328.359
      2374401.72       334035.39
#Sta/Elev= 30
       0  652.95     7.9   652.9    27.6  650.06    39.5  648.98    47.4  647.23
    67.1  644.87    98.7   639.6     146   634.9   161.8  632.45   197.6  630.52
   213.6  630.34   217.6  629.98   223.8  628.28   229.6  627.24   238.8  628.38
   241.6  628.92   261.5  629.87   297.5   629.8   305.5  631.25   313.5  631.75
   333.5  630.36   349.5  626.76   377.4  626.22   393.4  626.74   421.4  626.68
   425.4  627.19   429.4  628.47   437.4  632.13   441.4  633.03   481.4  633.86
#Mann= 3 , 0 , 0
       0      .1       0   223.8    .045       0   238.8      .1       0
Bank Sta=223.8,238.8
XS Rating Curve= 0 ,0
Exp/Cntr=0.3,0.1

Type RM Length L Ch R = 1 ,1214.2  ,225.6,227.8,228.2
XS GIS Cut Line= 2
     2374685.871      334380.808     2374527.337      333953.575
#Sta/Elev= 30
       0  653.59   58.33646.9753      68  646.26    80.5644.5497    83.9  644.14
    87.9  643.06    95.9  640.19   103.9   638.1   123.9  634.21   151.9  630.54
   179.9  628.92   183.9  628.45   188.2  627.32   191.9  626.33   195.9  625.95
   203.2  627.66   207.9   628.4   231.8  628.69   239.8  627.72   247.8  626.16
   251.8  626.06   263.8  627.54   271.8  627.85  314.78627.5323   355.8  628.87
   379.8  629.12   387.7  629.58   407.7  631.78  431.98633.3389   455.7  635.24
#Mann= 7 ,-1 , 0
       0     .12       0   58.33     .06       0    80.5     .12       0
   188.2    .045       0   203.2     .12       0  314.78     .06       0
  431.98     .12       0
#XS Ineff= 2 , 0
                          364.29          630.73
Permanent Ineff=
       F       F
Bank Sta=188.2,203.2
XS Rating Curve= 0 ,0
Exp/Cntr=0.3,0.1

Type RM Length L Ch R = 1 ,986.4   ,252,251.7,254.9
XS GIS Cut Line= 2
      2374872.64      334315.338     2374744.602      333913.862
#Sta/Elev= 30
       0  648.66    11.9  647.59    19.9  647.16    55.7  642.44    63.6  641.57
    79.5   640.4    99.4   639.3   135.2  636.45     167  632.22   174.9  630.11
   178.9  629.53   186.8  627.62   190.8  626.87   194.8  626.45   202.8  626.24
   222.6  626.39   230.6  625.58   238.5  624.69   246.5  625.22  248.43  625.65
   250.4  625.99   258.4  626.55   266.4  626.65     318  626.46     330  626.26
   353.8  626.64   385.6  626.51   393.6  626.76   401.5  627.46   421.4  631.02
#Mann= 3 , 0 , 0
       0      .1       0   230.6    .045       0  248.43      .1       0
#XS Ineff= 2 , 0
                          391.64          628.82
Permanent Ineff=
       F       F
Bank Sta=230.6,248.43
XS Rating Curve= 0 ,0
Exp/Cntr=0.3,0.1

Type RM Length L Ch R = 1 ,734.6   ,249.4,247.4,241.7
XS GIS Cut Line= 4
     2375055.663      334247.995     2375036.566      334063.967
     2374983.614      333895.565     2374921.983      333823.516
#Sta/Elev= 30
       0  656.55    11.8  654.74    23.6  654.21    27.6   653.5    47.2  651.77
    55.1  650.18    78.7  644.48  103.69 639.782   114.2  637.81  118.42637.3313
   165.3  632.91   177.1  630.97   200.7   628.1   216.4  625.73   232.1  624.64
   239.9   623.2   251.7  623.03   255.6  623.12   267.4  624.56   279.2  623.82
     287  624.24   306.6  624.47   314.5  625.39   322.3  626.98   349.8  630.98
   361.6  631.54   369.4  632.28   389.2  632.95     401  632.94   456.4  634.88
#Mann= 5 ,-1 , 0
       0     .12       0  103.69     .06       0  118.42     .12       0
   239.9    .045       0   255.6     .12       0
Bank Sta=239.9,255.6
XS Rating Curve= 0 ,0
Exp/Cntr=0.3,0.1

Type RM Length L Ch R = 1 ,487.2   ,230.8,233.4,235.3
XS GIS Cut Line= 3
     2375192.816      334150.773     2375250.244      334005.008
     2375117.866      333684.913
#Sta/Elev= 30
       0  645.16    35.2  642.12    50.9  639.58    58.8  637.48    74.4  634.53
      94  631.46   208.4  625.06   220.4  625.23   236.3  624.08   248.2  624.66
   252.2  623.94   257.7  621.59   260.2  620.69   264.2  620.15   268.2  620.42
  273.68  621.64   280.1  623.32   284.1  623.68     312  623.27   323.9  623.56
   339.8   622.9   355.7  623.38   387.6  622.67   399.5  624.12   423.4     625
   435.4  627.97   447.3  629.67   459.3  630.66   479.2  630.31   503.1  630.62
#Mann= 3 , 0 , 0
       0      .1       0   257.7    .045       0  273.68      .1       0
#XS Ineff= 2 , 0
                          396.28          626.13
Permanent Ineff=
       F       F
Bank Sta=257.7,273.68
XS Rating Curve= 0 ,0
Exp/Cntr=0.3,0.1

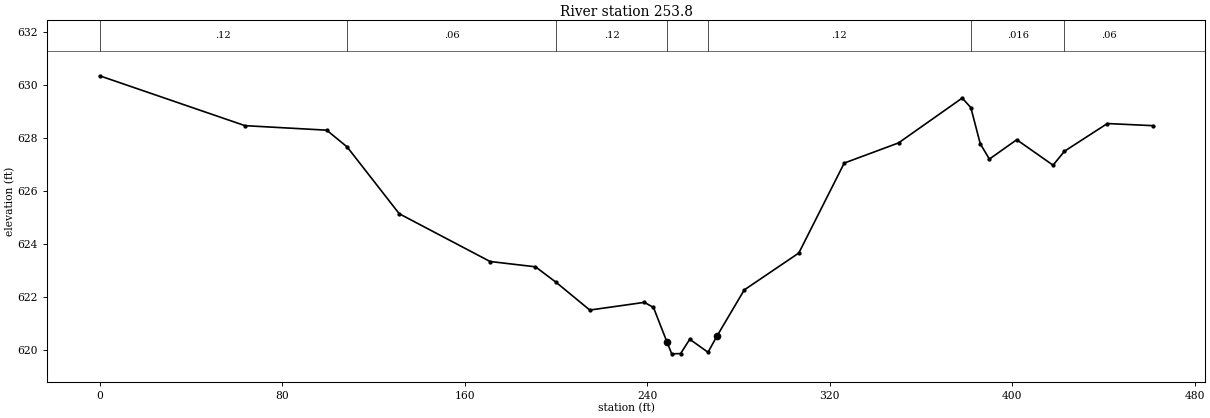
Type RM Length L Ch R = 1 ,253.8   ,251.9,253.8,252
XS GIS Cut Line= 2
     2375477.755      334030.656     2375300.672       333604.44
#Sta/Elev= 30
       0  630.34    63.7  628.46    99.5  628.29  108.44  627.66   131.3  625.14
   171.1  623.34     191  623.14  200.08622.5528   214.8  621.51   238.7   621.8
   242.7  621.61  248.53 620.325   250.7  619.86   254.6  619.87   258.6  620.41
   266.6  619.92   270.6  620.54   282.5  622.27   306.4  623.66   326.3  627.05
   350.1  627.81     378   629.5  381.78629.1409   385.9  627.78   389.9   627.2
   401.9  627.93   417.8  626.97  422.81627.4965   441.6  628.54   461.5  628.46
#Mann= 7 ,-1 , 0
       0     .12       0  108.44     .06       0  200.08     .12       0
  248.53    .045       0   266.6     .12       0  381.78    .016       0
  422.81     .06       0
Bank Sta=248.53,270.6
XS Rating Curve= 0 ,0
Exp/Cntr=0.3,0.1

Chan Stop Cuts=-1
Use User Specified Reach Order=0
Composite Channel Slope=5